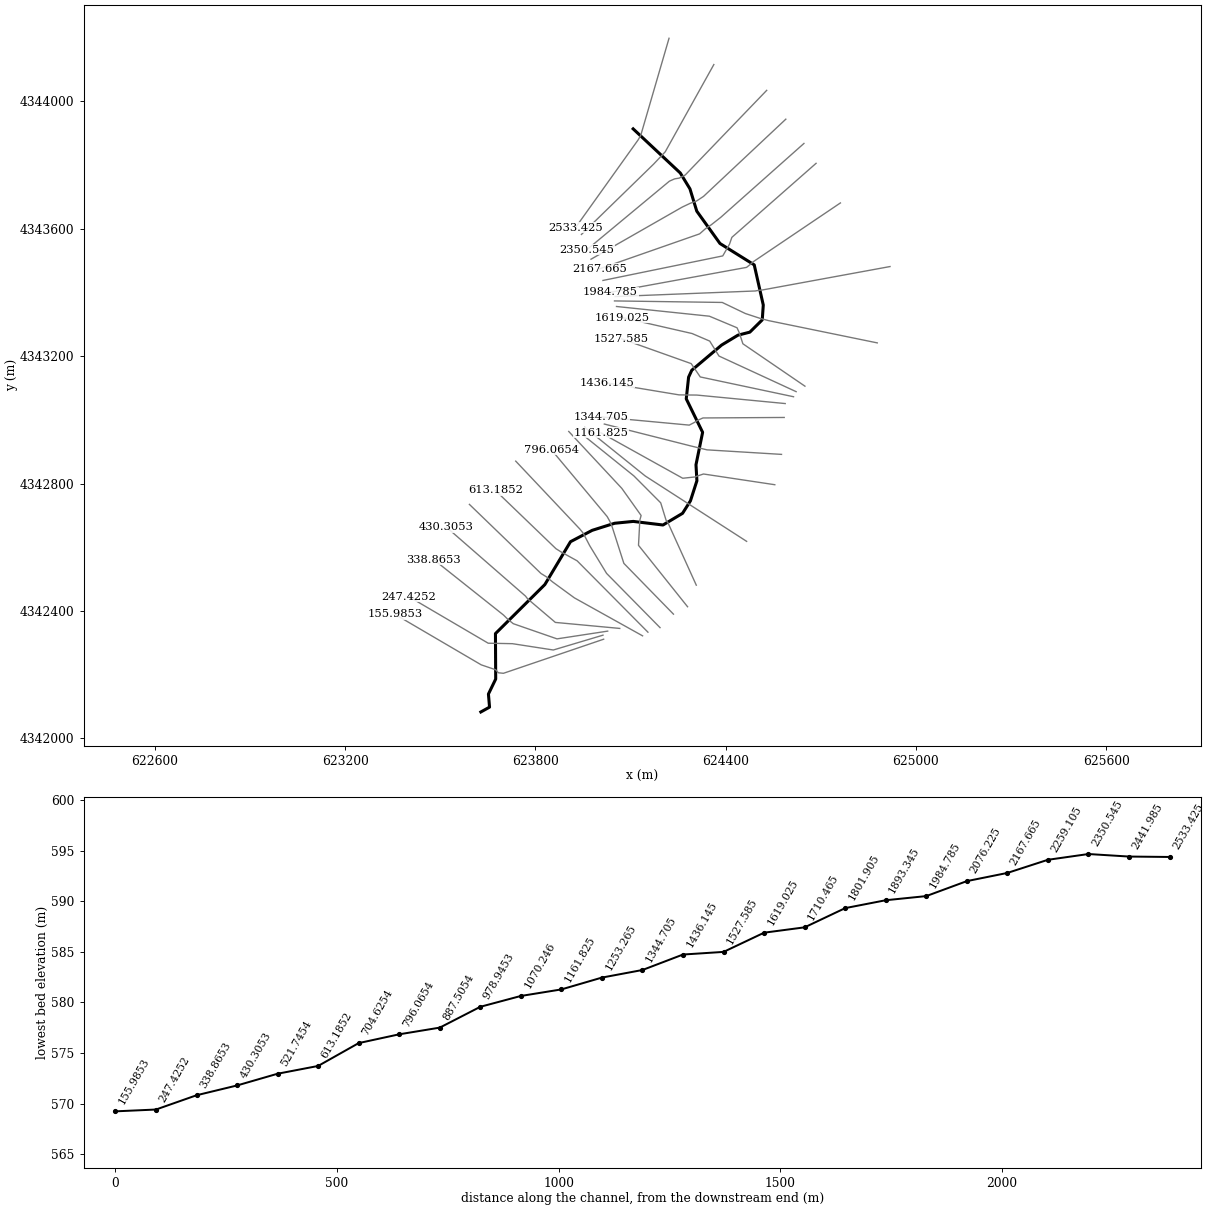
--- HorseshoeRun1.prj (project) ---

Proj Title=HorseshoeRun1
Current Plan=p01
Default Exp/Contr=0.3,0.1
SI Units
Geom File=g01
Flow File=f01
Plan File=p01
Background Map Layer=Google Hybrid
Y Axis Title=Elevation
X Axis Title(PF)=Main Channel Distance
X Axis Title(XS)=Station
BEGIN DESCRIPTION:
September 2018
Tucker County ABFE Study
US Army Corps of Engineers, Pittsburgh District
NAD 1983 UTM 17N (meters)
END DESCRIPTION:
DSS Export Rating Curves= 0
DSS Export Rating Curve Sorted= 0
DSS Export Volume Flow Curves= 0
DXF OffsetX= 0
DXF OffsetY= 0
DXF ScaleX= 1
DXF ScaleY= 10

--- HorseshoeRun1.p01 (plan) ---

Plan Title=HorseshoeRun1_plan
Program Version=5.05
Short Identifier=Plan1_subcritical
Geom File=g01
Flow File=f01
Subcritical Flow
K Sum by GR= 0
Std Step Tol= 0.003
Critical Tol= 0.003
Num of Std Step Trials= 20
Max Error Tol= 0.1
Flow Tol Ratio= 0.001
Split Flow NTrial= 30
Split Flow Tol= 0.006
Split Flow Ratio= 0.02
Log Output Level= 0
Friction Slope Method= 1
Unsteady Friction Slope Method= 2
Unsteady Bridges Friction Slope Method= 1
Parabolic Critical Depth
Global Vel Dist= 0 , 0 , 0
Global Log Level= 0
CheckData=True
Encroach Param=-1 ,0,0, 0
Computation Interval=1MIN
Output Interval=1HOUR
Instantaneous Interval=1HOUR
Mapping Interval=1HOUR
Computation Time Step Use Courant=        0
Computation Time Step Use Time Series=    0
Computation Time Step Count To Double=0
Computation Time Step Max Doubling=0
Computation Time Step Max Halving=0
Computation Time Step Residence Courant=0
Run HTab= 0
Run UNet= 0
Run Sediment= 0
Run PostProcess= 0
Run WQNet= 0
Run RASMapper=-1
UNET Theta= 1
UNET Theta Warmup= 1
UNET ZTol= 0.006
UNET ZSATol= 0.006
UNET MxIter= 20
UNET Max Iter WO Improvement= 0
UNET MaxInSteps= 0
UNET DtIC= 0
UNET DtMin= 0
UNET MaxCRTS= 20
UNET WFStab= 2
UNET SFStab= 1
UNET WFX= 1
UNET SFX= 1
UNET 1D Methodology=Finite Difference
UNET DSS MLevel= 4
UNET Pardiso=0
UNET DZMax Abort= 30
UNET Use Existing IB Tables=-1
UNET Froude Reduction=False
UNET Froude Limit= 0.8
UNET Froude Power= 4
UNET D1 Cores= 0
UNET D2 Coriolis=0
UNET D2 Cores= 0
UNET D2 Theta= 1
UNET D2 Theta Warmup= 1
UNET D2 Z Tol= 0.003
UNET D2 Volume Tol= 0.003
UNET D2 Max Iterations= 20
UNET D2 Equation= 0
UNET D2 RampUpFraction=0.1
UNET D2 TimeSlices= 1
UNET D2 BCVolumeCheck=0
UNET D1D2 MaxIter= 0
UNET D1D2 ZTol=0.003
UNET D1D2 QTol=0.1
UNET D1D2 MinQTol=0.03
Write IC File= 0
Write IC File at Fixed DateTime=0
Write IC File at Sim End=0
Echo Input=False
Echo Parameters=False
Echo Output=False
Write Detailed= 0
HDF Write Warmup=0
HDF Write Time Slices=0
HDF Flush=0
HDF Face Node Velocities=0
HDF Compression= 1
HDF Chunk Size= 1
HDF Spatial Parts= 1
HDF Use Max Rows=0
HDF Fixed Rows= 1
Calibration Method= 0
Calibration Iterations= 20
Calibration Max Change=0.05
Calibration Tolerance=0.2
Calibration Maximum=1.5
Calibration Minimum=0.5
Calibration Optimization Method= 1
WQ AD Non Conservative
WQ ULTIMATE=-1
WQ Max Comp Step=1HOUR
WQ Output Interval=15MIN
WQ Output Selected Increments= 0
WQ Output face flow=0
WQ Output face velocity=0
WQ Output face area=0
WQ Output face dispersion=0
WQ Output cell volume=0
WQ Output cell surface area=0
WQ Output cell continuity=0
WQ Output cumulative cell continuity=0
WQ Output face conc=0
WQ Output face dconc_dx=0
WQ Output face courant=0
WQ Output face peclet=0
WQ Output face adv mass=0
WQ Output face disp mass=0
WQ Output cell mass=0
WQ Output cell source sink temp=0
WQ Output nsm pathways=0
WQ Output nsm derived pathways=0
WQ Output MaxMinRange=-1
WQ Daily Max Min Mean=-1
WQ Daily Range=0
WQ Daily Time=0
WQ Create Restart=0
WQ Fixed Restart=0
WQ System Summary=0
WQ Write To DSS=0
WQ Use Fixed Temperature=0
Sorting and Armoring Iterations= 10
XS Update Threshold= 0.02
Bed Roughness Predictor= 0
Hydraulics Update Threshold= 0.02
Energy Slope Method= 1
Volume Change Method= 1
Sediment Retention Method= 0
XS Weighting Method= 0
Number of US Weighted Cross Sections= 1
Number of DS Weighted Cross Sections= 1
Upstream XS Weight=0
Main XS Weight=1
Downstream XS Weight=0
Number of DS XS's Weighted with US Boundary= 1
Upstream Boundary Weight= 1
Weight of XSs Associated with US Boundary= 0
Number of US XS's Weighted with DS Boundary= 1
Downstream Boundary Weight= 0.5
Weight of XSs Associated with DS Boundary= 0.5
Percentile Method= 0
Sediment Output Level= 4
Mass or Volume Output= 0
Output Increment Type= 1
Profile and TS Output Increment= 1
XS Output Flag= 0
XS Output Increment= 10
Write Gradation File= 0
Read Gradation Hotstart= 0
Write HDF5 File= 1
Write Binary Output= 1
Write DSS Sediment File= 0
SV Curve= 0
Specific Gage Flag= 0

--- HorseshoeRun1.f01 (steady flow) ---

Flow Title=HorseshoeRun1_flow
Program Version=5.05
Number of Profiles= 1
Profile Names=PF 1
River Rch & RM=Horseshoe Run,8               ,2533.425
 46.0994
River Rch & RM=Horseshoe Run,8               ,1161.825
 56.0385
River Rch & RM=Horseshoe Run,8               ,155.9853
  57.426
Boundary for River Rch & Prof#=Horseshoe Run,8               , 1
Up Type= 2
Dn Type= 1
Dn Known WS=572.7
DSS Import GetInterval= 0
DSS Import GetPeak= 0
DSS Import FillOption= 0

--- HorseshoeRun1.g01 (geometry) ---

Geom Title=HorseshoeRun1_geometry
Program Version=5.05

River Reach=Horseshoe Run   ,8
Reach XY= 30
     624108.1555    4343914.0392624256.8075397024343775.45122557
624287.2892908474343725.63164886     624308.8114    4343655.6013
      624381.953    4343554.1024       624489.95    4343487.0009
     624518.4782    4343360.9562     624515.3032    4343314.3894
     624476.1448    4343275.7602     624438.5739    4343266.2352
     624387.1485    4343235.2548     624293.0528    4343156.1683
     624282.9986    4343134.4724     624275.6211    4343066.3369
     624327.2282    4342961.2141      624306.282    4342859.3052
     624309.2014    4342809.1371     624288.8195    4342746.0633
     624263.9486    4342706.9049     624202.2476    4342670.2336
     624108.4577    4342681.4942     624049.6356     4342675.684
     623979.0219    4342653.5015     623910.5728    4342617.7762
623829.6749187074342483.20383015     623673.9266    4342329.2114
     623674.7203    4342186.5842     623651.7931    4342139.4742
     623655.2734    4342098.3289     623627.8152    4342083.1662

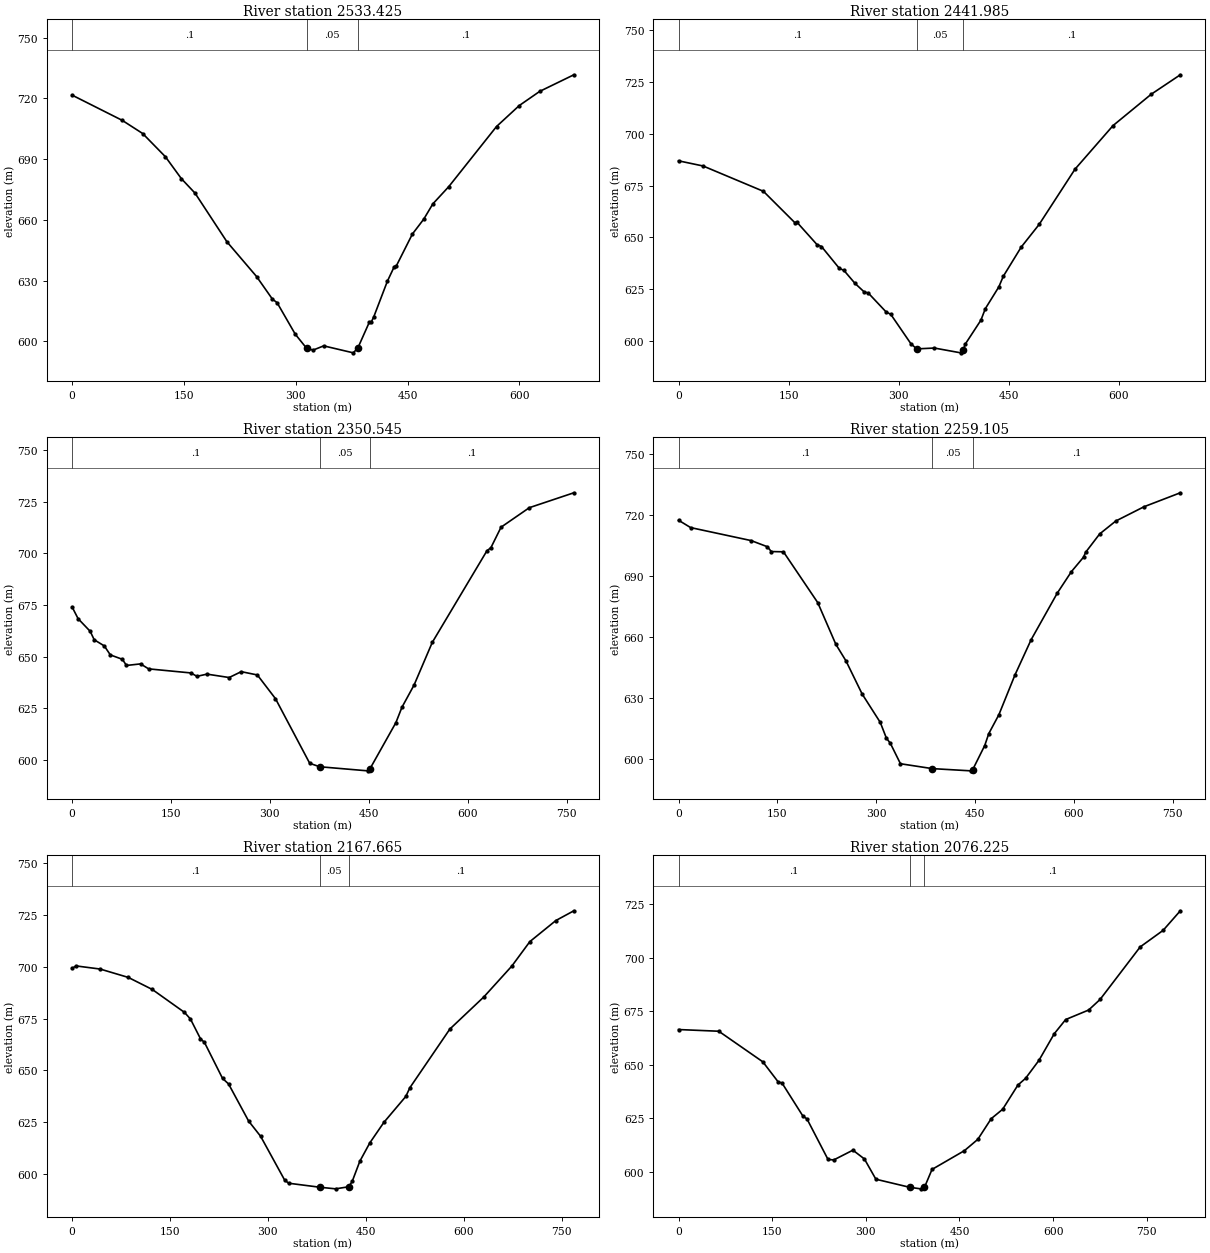
Type RM Length L Ch R = 1 ,2533.425,94.37,91.44,87.25
XS GIS Cut Line= 4
     624221.3076    4344198.4882     624132.0918    4343893.5663
     624123.6325    4343879.0872     623926.2966    4343603.9683
#Sta/Elev= 30
       0  721.64   67.21  709.19    94.7  702.68  125.25  691.19  146.63  680.38
  164.96  673.23  207.73  649.21  247.44  632.08  268.83  620.85  274.94  619.19
  299.38  603.59  314.65  596.61   323.3  595.75  337.52  597.83  377.18  594.39
  383.28  596.77  398.53  609.37  401.58  609.79  404.63  612.12  422.93  629.75
  432.08  636.89  435.13  637.45  456.48  653.05  471.73  660.41  483.94  667.95
  505.29  676.46  569.34  706.14  599.84  716.49  627.29  723.49  673.05  731.68
#Mann= 3 , 0 , 0
       0      .1       0  314.65     .05       0  383.28      .1       0
Bank Sta=314.65,383.28
XS Rating Curve= 0 ,0
Exp/Cntr=0.3,0.1

Type RM Length L Ch R = 1 ,2441.985,93.28,91.44,79.11
XS GIS Cut Line= 4
     624362.5954     4344115.938     624209.4038    4343842.1351
     624173.2063    4343803.8249      623945.082     4343582.537
#Sta/Elev= 30
       0  686.88   33.51  684.39  115.75   672.2   158.4  657.18  161.44  657.33
  188.86  646.53  194.95  645.62  219.32  635.08  225.41  634.17  240.64  627.87
  252.82  623.87  258.92  623.16  283.28  614.04  289.38  612.99  316.67  598.92
  324.64  596.33  348.88  596.74  384.79  594.43  387.84  595.56   390.9  598.57
  412.29  610.13   418.4  615.72  436.74  626.16  442.85  631.28   467.3  645.35
  491.74  656.25  540.64  682.86  592.59  703.87  644.54  718.93  684.27  728.31
#Mann= 3 , 0 , 0
       0      .1       0  324.64     .05       0  387.84      .1       0
Bank Sta=324.64,387.84
XS Rating Curve= 0 ,0
Exp/Cntr=0.3,0.1

Type RM Length L Ch R = 1 ,2350.545,90.41,91.44,92.2
XS GIS Cut Line= 6
     624529.2832    4344034.9754     624272.4007    4343769.2044
     624253.4683    4343759.4228     624239.0173    4343757.0704
      624222.608      4343749.88     623962.5446    4343534.9119
#Sta/Elev= 30
       0  674.04    9.16  668.33   27.49  662.21    33.6  658.13   48.88  655.15
   58.04   650.8   76.37  648.66   82.48  645.69  103.86  646.45  116.08  644.04
  180.23  642.07  189.39  640.43  204.67  641.49  238.27  639.85   256.6  642.69
  281.04  641.09  308.53  629.61  360.46  598.32  375.55  596.66  448.21  594.68
  451.27  595.35  491.15  618.01  500.35  625.46  518.76  636.24  546.36  656.87
  629.18  701.17  635.31  702.73  650.65  712.62  693.59  722.07  761.08  729.28
#Mann= 3 , 0 , 0
       0      .1       0  375.55     .05       0  451.27      .1       0
Bank Sta=375.55,451.27
XS Rating Curve= 0 ,0
Exp/Cntr=0.3,0.1

Type RM Length L Ch R = 1 ,2259.105,87.93,91.44,95.57
XS GIS Cut Line= 6
     624589.6083    4343944.4877      624330.053    4343701.9833
     624307.6348    4343687.1753     624288.2232    4343680.3837
     624262.5204    4343668.2154     623975.2446    4343504.7493
#Sta/Elev= 30
       0  717.49   18.37  713.86  110.24  707.46  134.74  704.45  140.86  702.06
  159.23  701.94  211.29  676.93  238.85  656.34  254.16  648.23  278.66  631.94
  306.22  617.94  315.41  610.26  321.53  607.64  336.84   597.6  385.02  595.21
  443.33  594.11  446.39  594.63  464.75  606.58  470.87  612.44  486.17   621.7
  510.66  641.34  535.14  658.65  574.93  681.65  596.35   692.2  614.71  699.31
  617.77  701.65   639.2  710.74  663.68   717.1  706.53  724.13  761.61     731
#Mann= 3 , 0 , 0
       0      .1       0  385.02     .05       0  446.39      .1       0
Bank Sta=385.02,446.39
XS Rating Curve= 0 ,0
Exp/Cntr=0.3,0.1

Type RM Length L Ch R = 1 ,2167.665,97.2,91.44,97.87
XS GIS Cut Line= 6
     624646.7585    4343868.2875     624384.2362    4343636.1184
      624354.206    4343612.6706     624336.5293    4343600.8191
       624317.73    4343584.3721     624002.2322    4343474.5868
#Sta/Elev= 30
       0   699.2    6.15  700.38   43.04  698.87   86.08  694.84  122.97  689.01
  172.15  677.98  181.38  674.77  196.75  665.23   202.9  663.45  230.56  646.11
  239.79  643.42  270.53  625.52  288.97  618.13  325.86  596.96  332.01  595.51
  379.77  593.58  403.76  592.81  423.72   593.8  429.27  596.42  440.95  606.14
  456.27     615  477.72  624.86  511.44  637.42  517.57  641.59  578.86  669.91
  630.96  685.42  673.87  700.33  701.45  712.11  741.29  722.28  768.87  726.99
#Mann= 3 , 0 , 0
       0      .1       0  379.77     .05       0  423.72      .1       0
Bank Sta=379.77,423.72
XS Rating Curve= 0 ,0
Exp/Cntr=0.3,0.1

Type RM Length L Ch R = 1 ,2076.225,99.39,91.44,88.04
XS GIS Cut Line= 5
     624684.9908    4343805.8457     624419.4233    4343573.3762
      624411.999    4343551.9123     624390.7128    4343515.1451
     624012.9478    4343438.0742
#Sta/Elev= 30
       0  666.48   64.45  665.69  135.04  651.38  159.59     642  165.73  641.48
  199.49  625.89  205.63  624.74  239.39  605.75  248.59  605.51  279.28  610.08
   297.7  605.97  316.11  596.49  369.98  592.74  387.79     592  393.86  592.67
     406  601.08  457.92  609.86  479.34  615.14  500.76   624.8  519.11   629.2
  543.59  640.53  555.83  643.67  577.25  652.06  601.73  664.51  620.09  671.16
  656.81   675.6  675.17  680.55  739.43  705.12  776.15  712.86  803.69  722.01
#Mann= 3 , 0 , 0
       0      .1       0  369.98     .05       0  393.86      .1       0
Bank Sta=369.98,393.86
XS Rating Curve= 0 ,0
Exp/Cntr=0.3,0.1

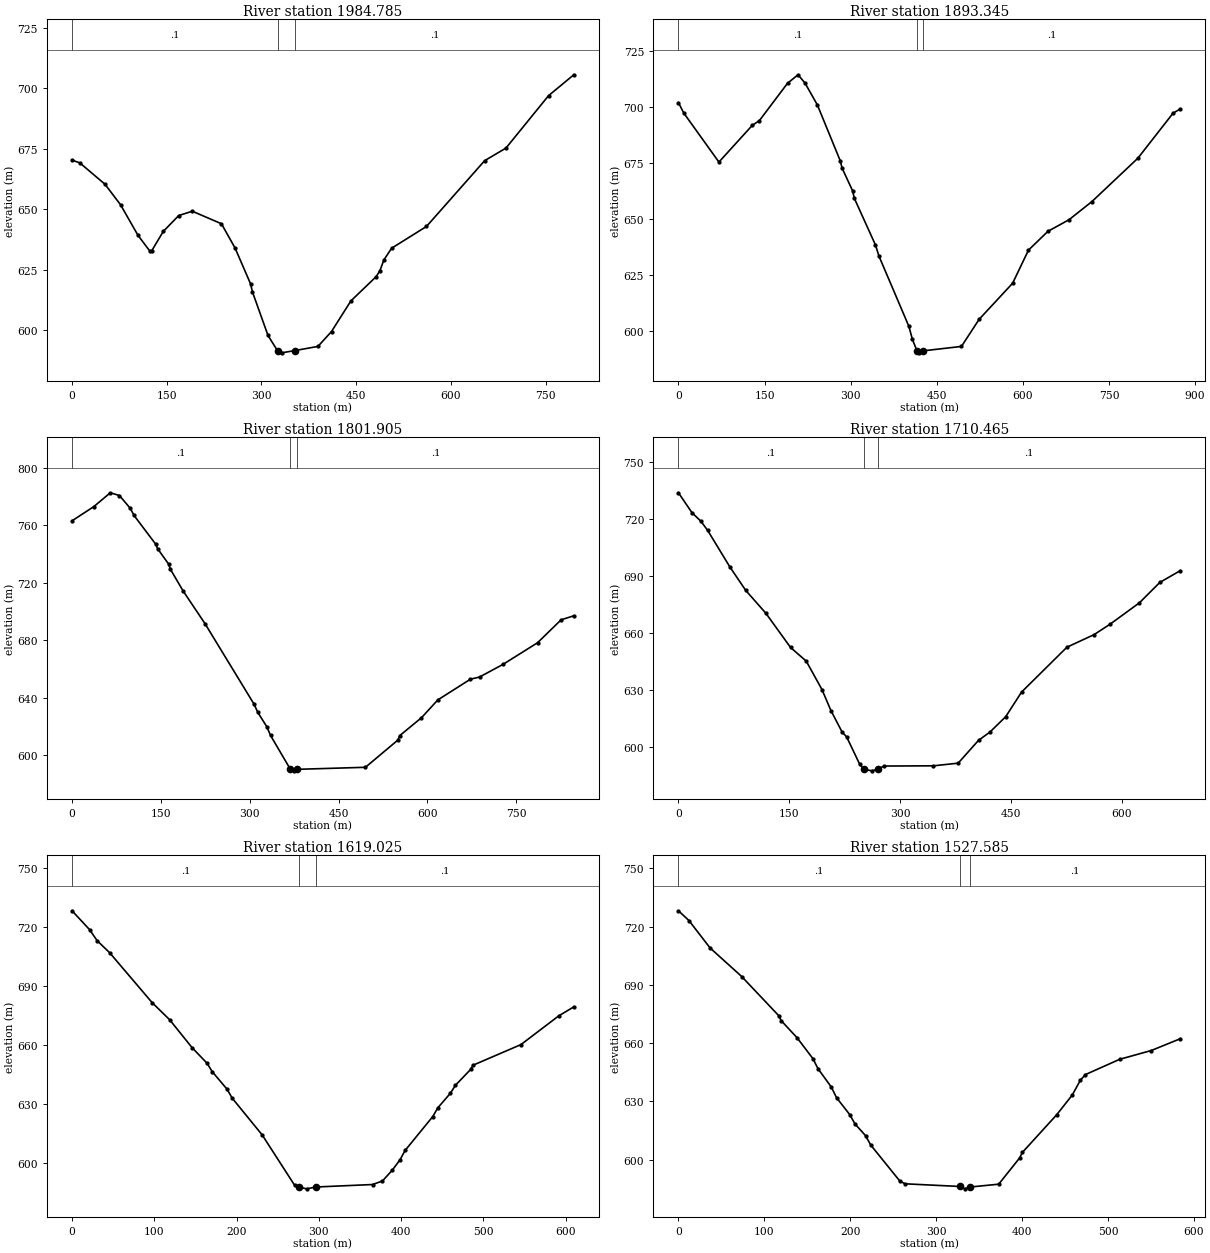
Type RM Length L Ch R = 1 ,1984.785,95.62,91.44,85.72
XS GIS Cut Line= 5
     624761.7201    4343681.4913     624486.2548    4343496.3991
     624478.2784    4343488.9337      624465.677    4343479.0917
     624036.7604    4343401.0324
#Sta/Elev= 30
       0  670.33   12.29  669.19   52.24  660.32   76.82  651.84  104.48  639.16
  122.92  632.76  125.99   632.7  144.43  640.79  169.01  647.39  190.52  649.17
  236.61  643.98  258.12  633.97  282.71  619.11  285.78  615.72  310.36  597.73
  325.73  591.25  331.87  590.52  353.46  591.48  389.49  593.18  410.98  599.35
  441.68  612.03  481.59  622.05  487.73  624.56  493.87  628.97  506.16  633.84
  561.42  642.87  653.52   670.1  687.29  675.32  754.84  697.05  794.75  705.68
#Mann= 3 , 0 , 0
       0      .1       0  325.73     .05       0  353.46      .1       0
Bank Sta=325.73,353.46
XS Rating Curve= 0 ,0
Exp/Cntr=0.3,0.1

Type RM Length L Ch R = 1 ,1893.345,93.99,91.44,87.29
XS GIS Cut Line= 6
     624918.2215    4343481.7305     624514.3138     4343407.928
     624509.5156    4343407.6952     624502.2534    4343406.7706
      624493.602     4343405.043     624051.4448    4343387.5387
#Sta/Elev= 30
       0  701.89    9.19  697.26   70.48  675.33  128.69  691.76  140.95  693.84
  189.98  710.53  208.36  714.33  220.62  710.57  242.07  700.82   281.9  675.87
  284.97   672.7  303.35   662.5  306.41  659.13  343.18   638.3  349.31  633.31
   401.4  601.95  407.53  596.14   415.4  591.07  419.57  590.11  425.67  590.99
  493.01  592.97  523.74  605.07  582.12   621.2  609.78     636  643.58  644.38
  680.46  649.59  720.41  657.71   800.3  677.05  861.76  697.22  874.05  699.01
#Mann= 3 , 0 , 0
       0      .1       0   415.4     .05       0  425.67      .1       0
Bank Sta=415.4,425.67
XS Rating Curve= 0 ,0
Exp/Cntr=0.3,0.1

Type RM Length L Ch R = 1 ,1801.905,97.14,91.44,80.09
XS GIS Cut Line= 6
     624878.0047    4343242.0175     624534.6623     4343312.062
     624509.0134    4343318.8598     624462.1142    4343334.2006
     624389.0538    4343369.0178     624049.3281    4343373.7803
#Sta/Elev= 30
       0  762.99   36.89   772.9   64.55  782.46   79.92  780.57   98.36  771.63
  104.51  766.77   141.4  746.65  144.47  743.61  162.91     733  165.99  729.37
   187.5  714.25  224.39  691.59  307.38  635.54  313.53  629.95   328.9  619.88
  335.05  613.91  368.67  590.34  374.22  589.33  379.89  590.38  495.28  591.79
  550.12  610.73  553.18  613.79  589.91  626.22  617.46  638.59  672.56  652.98
  687.86  654.48  727.65   663.3  785.81  678.29   825.6  694.21  847.03  697.02
#Mann= 3 , 0 , 0
       0      .1       0  368.67     .05       0  379.89      .1       0
Bank Sta=368.67,379.89
XS Rating Curve= 0 ,0
Exp/Cntr=0.3,0.1

Type RM Length L Ch R = 1 ,1710.465,89.81,91.44,94.03
XS GIS Cut Line= 6
     624649.8805    4343106.1008     624454.1364    4343239.2626
     624443.1262    4343273.1229     624435.7715    4343289.4765
     624348.5698    4343325.8325     624055.6781    4343356.3178
#Sta/Elev= 30
       0  733.58   18.21  723.16   30.35  718.63   39.46  713.85   69.81  694.48
   91.06  682.28  118.37  670.24  151.76  652.27  173.01  645.09  194.25  630.18
  206.39  619.13  221.57  607.81  227.64  605.31  245.17  591.06   250.8  588.28
  262.04  587.43   269.8  588.35  278.36  589.95  345.17  590.07  378.69  591.46
  406.26  603.48   421.6  607.77  443.07  615.91  464.54  628.84  525.89  652.41
   562.7  659.03  584.17  664.46  624.05  675.74  651.66  686.45  679.26  692.62
#Mann= 3 , 0 , 0
       0      .1       0   250.8     .05       0   269.8      .1       0
Bank Sta=250.8,269.8
XS Rating Curve= 0 ,0
Exp/Cntr=0.3,0.1

Type RM Length L Ch R = 1 ,1619.025,89.7,91.44,90.08
XS GIS Cut Line= 5
     624622.0992    4343088.9029     624378.9292    4343200.6786
     624349.5251    4343247.7254     624293.9986    4343271.4267
     624073.0877    4343321.7367
#Sta/Elev= 30
       0  728.12   21.29  718.54   30.41  712.99   45.62  706.85   97.32  681.49
  118.61   672.8  145.98  658.58  164.23  650.65  170.31  646.47  188.56  637.45
  194.64  632.99  231.13   614.3  270.55  588.75  276.39  587.79  285.15   586.9
  296.83  587.84  365.37  589.09  377.45   590.9  389.61  596.51  398.79  601.66
  404.91  606.38  438.59  623.62  444.72  628.03  460.03  635.46  466.15  639.49
  484.52  647.52  487.58   649.7  545.75  660.15  591.68  674.73  610.05  679.31
#Mann= 3 , 0 , 0
       0      .1       0  276.39     .05       0  296.83      .1       0
Bank Sta=276.39,296.83
XS Rating Curve= 0 ,0
Exp/Cntr=0.3,0.1

Type RM Length L Ch R = 1 ,1527.585,81.71,91.44,96.41
XS GIS Cut Line= 4
     624613.8971    4343072.9749     624319.8166    4343135.0847
     624291.1103    4343176.9804     624071.7648     4343254.744
#Sta/Elev= 30
       0  728.13   12.27  723.07    36.8     709   73.61  694.29  116.55  674.22
  119.61  671.57  138.02  662.81  156.42  652.09  162.55  646.78  177.89  637.43
  184.02  631.93  199.36  623.23  205.49  618.43  217.76  612.39  223.89  607.52
  257.63  589.05  263.76  587.59  327.46  586.22  333.43     585   339.4  585.93
  372.79  587.39  397.29  600.96  400.35  603.74  440.16  623.05  458.53  633.34
  467.72  640.81  473.84  643.83  513.65  651.68  550.39   656.2  584.08  662.24
#Mann= 3 , 0 , 0
       0      .1       0  327.46     .05       0   339.4      .1       0
Bank Sta=327.46,339.4
XS Rating Curve= 0 ,0
Exp/Cntr=0.3,0.1

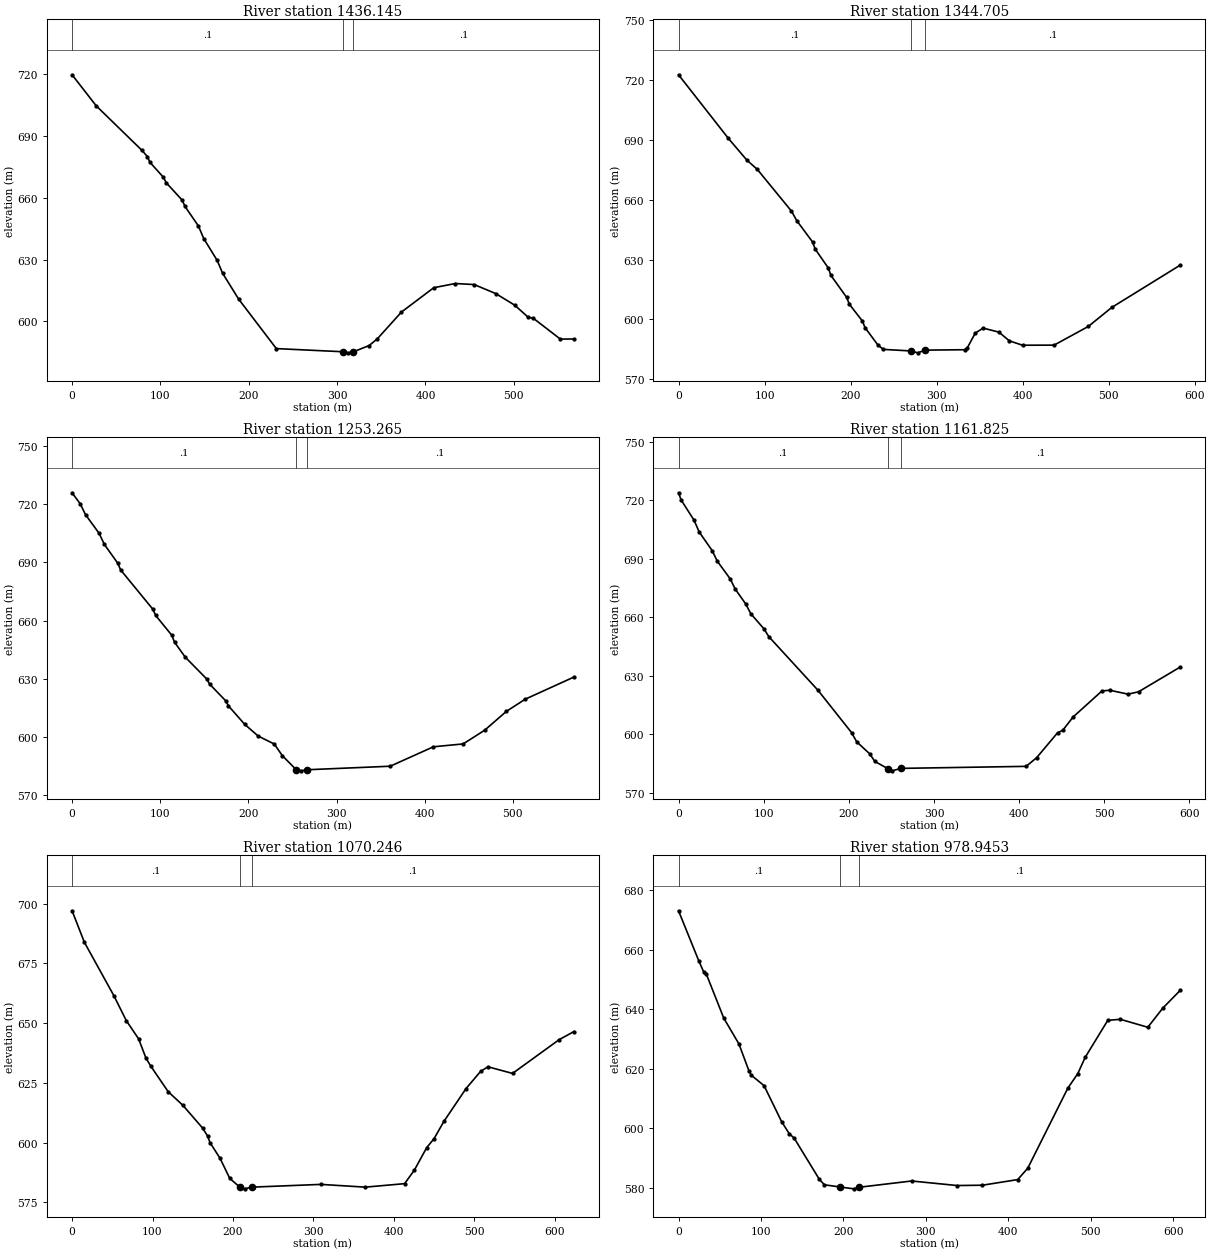
Type RM Length L Ch R = 1 ,1436.145,83.88,91.44,93.29
XS GIS Cut Line= 4
     624587.7033    4343051.5436     624309.1014    4343078.1739
      624252.752       4343078.8     624024.1397    4343116.6312
#Sta/Elev= 30
       0  719.73   27.38  704.64   79.09  683.04   85.18  680.05   88.22   677.2
  103.43  669.95  106.47  667.37  124.73  658.82  127.77  655.84  142.98  646.35
  149.06  640.19  164.27   629.6  170.36  623.39  188.61  610.78   231.2   586.8
  306.57  585.27   312.5  584.74  318.43  585.25  336.22  588.28  345.37  591.48
  372.81  604.54   409.4  616.36  433.79  618.39  455.13  617.89  479.53  613.51
  500.87  607.92  516.11  602.08  522.21  601.47   552.7   591.4  567.95  591.48
#Mann= 3 , 0 , 0
       0      .1       0  306.57     .05       0  318.43      .1       0
Bank Sta=306.57,318.43
XS Rating Curve= 0 ,0
Exp/Cntr=0.3,0.1

Type RM Length L Ch R = 1 ,1344.705,94.81,91.44,83.23
XS GIS Cut Line= 6
     624584.5283    4343007.8873       624328.13    4343006.3331
     624310.8466    4342998.5246     624301.8982    4342992.5997
     624285.1351    4342983.8435     624008.2647    4343009.4748
#Sta/Elev= 30
       0  722.74      58  690.77   79.36  679.93   91.57  675.24  131.25  654.31
  137.36  649.56  155.67  638.88  158.73  635.31  173.99  625.81  177.04  622.07
  195.35  611.04  198.41  607.64  213.67  599.15  216.72  595.83  231.98  586.97
  238.09  584.94  269.95  584.16  278.05  583.21   286.1  584.56  332.51  584.78
  335.57  585.71  344.73  593.09   353.9  595.63  372.23   593.6  384.46  589.21
  399.73  587.03   436.4  587.08  476.12  596.45  503.62  606.05  583.07  627.25
#Mann= 3 , 0 , 0
       0      .1       0  269.95     .05       0   286.1      .1       0
Bank Sta=269.95,286.1
XS Rating Curve= 0 ,0
Exp/Cntr=0.3,0.1

Type RM Length L Ch R = 1 ,1253.265,88.09,91.44,101.79
XS GIS Cut Line= 4
     624576.0616    4342891.9466      624341.001    4342906.1982
     624290.5659    4342918.3028     624017.2605    4342987.1968
#Sta/Elev= 30
       0  725.91    9.18  720.26   15.29  714.59   30.58  705.05    36.7  699.23
   51.99  689.48   55.05  686.13   91.75  665.78   94.81  662.63  113.16  652.38
  116.22  648.83  128.45  641.08  152.92  629.78  155.98  627.22  174.33  618.57
  177.38  615.97  195.73   606.5  211.03  600.43  229.38  596.28  238.54  590.29
  254.22  583.06   259.9  582.46     266  583.01  360.89  584.84  409.91  594.87
  443.61  596.34  468.11  603.44  492.62  613.12  514.07  619.43  569.21  630.83
#Mann= 3 , 0 , 0
       0      .1       0  254.22     .05       0     266      .1       0
Bank Sta=254.22,266
XS Rating Curve= 0 ,0
Exp/Cntr=0.3,0.1

Type RM Length L Ch R = 1 ,1161.825,96.12,91.58,84.18
XS GIS Cut Line= 6
     624554.8949    4342796.6964      624329.886    4342830.3785
     624309.8278     4342823.715     624303.8535    4342821.1641
       624264.47    4342817.0124     624006.6772    4342959.6801
#Sta/Elev= 30
       0   723.8    3.03  720.12    18.2  709.77   24.27   703.7   39.44   694.2
    45.5  688.76   60.67  679.69   66.74  674.33   78.87  666.86   84.94  661.78
  100.11  654.19  106.17     650  163.81  622.58  203.25  600.87  209.31  596.15
  224.48  590.03  230.54  586.15  245.63  582.44  250.82  581.29  261.24  582.55
  408.31  583.59  420.58  588.01  445.14  600.77  451.28  602.08  463.55  608.92
  497.31  622.23  506.52   622.6     528  620.59  540.28   621.8  589.39  634.52
#Mann= 3 , 0 , 0
       0      .1       0  245.63     .05       0  261.24      .1       0
Bank Sta=245.63,261.24
XS Rating Curve= 0 ,0
Exp/Cntr=0.3,0.1

Type RM Length L Ch R = 1 ,1070.246,96.52,91.3,88.09
XS GIS Cut Line= 3
     624465.9948    4342618.8961     624146.3044    4342824.0993
     623955.8771    4342976.6135
#Sta/Elev= 30
       0  697.03   15.32  683.84   52.08  661.42    67.4  651.06   82.72  643.43
   91.91  635.32   98.03  631.91  119.48  621.32  137.86  615.57  162.37  606.04
   168.5  602.73  171.56  599.94  183.81  593.53  196.07  585.01  208.32  581.42
  214.45  580.64  223.64  581.35  309.42   582.5  364.56  581.35  413.43  582.81
  425.63  588.51  440.88  597.89  450.02  601.63  462.22  608.83  489.67  622.55
  507.97  629.84  517.12  631.72  547.61  628.95  605.56  643.08  623.86  646.45
#Mann= 3 , 0 , 0
       0      .1       0  208.32     .05       0  223.64      .1       0
Bank Sta=208.32,223.64
XS Rating Curve= 0 ,0
Exp/Cntr=0.3,0.1

Type RM Length L Ch R = 1 ,978.9453,95.28,91.44,85.71
XS GIS Cut Line= 6
     624307.2444    4342481.3125     624218.0166    4342677.0277
     624211.9452    4342685.3704     624195.0661    4342739.8318
     624110.5005    4342824.3197     623949.5271    4342953.3301
#Sta/Elev= 30
       0  673.05   24.41  656.32   30.51  652.49   33.56  651.87   54.91  636.93
   73.22   628.3   85.42  619.21   88.47  617.71  103.72  614.26  125.08  602.12
  134.23  598.13  140.33  596.58  170.84  582.73  176.94  580.93  195.24  580.22
  212.71  579.57  219.33  580.11  282.74  582.21  337.91  580.68  368.56  580.79
  411.38  582.68  423.51   586.5  472.05  613.38  484.18  618.29  493.28  623.83
  520.59  636.21  535.76  636.57  569.13  633.89  587.33  640.33  608.57  646.33
#Mann= 3 , 0 , 0
       0      .1       0  195.24     .05       0  219.33      .1       0
Bank Sta=195.24,219.33
XS Rating Curve= 0 ,0
Exp/Cntr=0.3,0.1

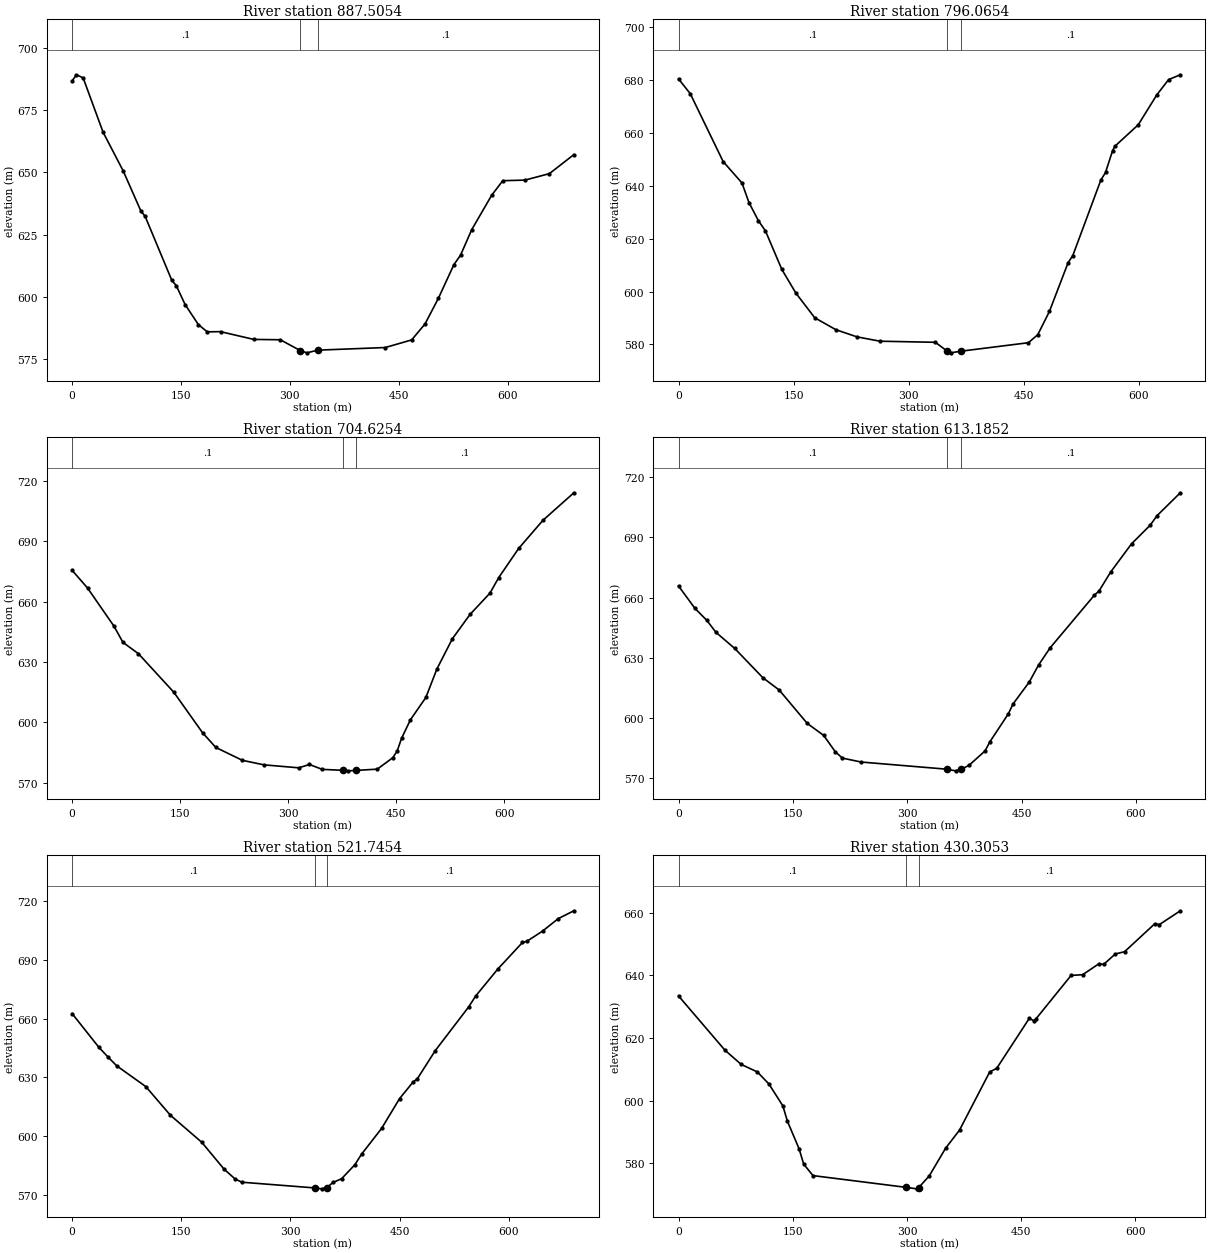
Type RM Length L Ch R = 1 ,887.5054,85.62,91.44,105.9
XS GIS Cut Line= 6
     624279.7277     4342413.579     624125.0436    4342606.4433
     624129.2506    4342685.5131       624133.28    4342700.0901
     624072.3939    4342785.2754      623905.077    4342963.9134
#Sta/Elev= 30
       0  686.68     6.1  689.13   15.26  687.88   42.73  666.06    70.2  650.67
   94.62  634.54  100.72  632.24  137.35  606.61  143.46  604.52  155.66   596.9
  173.98  588.82  186.19  585.94   204.5  586.01  250.28   582.9  286.82  582.76
  314.23  578.42  323.37  577.51  338.51  578.59  431.29  579.64  467.66   582.7
  486.02   589.1  504.38  599.36  525.79  612.91  534.97  616.72  550.27  626.91
   577.8  640.76   593.1  646.61  623.69  646.85  657.35  649.45     691  657.08
#Mann= 3 , 0 , 0
       0      .1       0  314.23     .05       0  338.51      .1       0
Bank Sta=314.23,338.51
XS Rating Curve= 0 ,0
Exp/Cntr=0.3,0.1

Type RM Length L Ch R = 1 ,796.0654,89.59,91.44,91.78
XS GIS Cut Line= 6
     624235.2776    4342390.2956     624078.8284    4342549.7864
     624041.9821    4342664.2985     624034.5963    4342681.8843
     624026.2658    4342696.6836     623850.0435    4342906.7633
#Sta/Elev= 30
       0  680.24    15.3  674.66   58.15  649.04   82.63  640.98   91.81  633.57
  104.06  626.73  113.24   622.9  134.66  608.31  153.02  599.36  177.51  590.09
  205.05  585.58  232.44  582.89  262.51  581.24  334.69  580.83  350.29  577.46
  354.61  576.85  368.47  577.49  455.96  580.67  468.14  583.67  483.38  592.48
  507.75   610.9  513.84  613.55   550.4  642.06   556.5  644.92  565.64  653.11
  568.68  654.81  599.15  662.93  623.53   674.3  638.76  679.99  653.99   681.8
#Mann= 3 , 0 , 0
       0      .1       0  350.29     .05       0  368.47      .1       0
Bank Sta=350.29,368.47
XS Rating Curve= 0 ,0
Exp/Cntr=0.3,0.1

Type RM Length L Ch R = 1 ,704.6254,84.28,91.44,94.1
XS GIS Cut Line= 6
     624192.9442    4342347.9622      624024.444    4342518.1552
     623971.1662    4342605.2655      623950.644     4342644.612
     623940.4083      4342657.19       623737.86    4342870.7799
#Sta/Elev= 30
       0   675.6   21.49  666.77   58.34  647.74   70.62  639.79   92.11  634.16
  141.24  615.03  181.16  594.89  199.58  587.59  236.42   581.2  266.52  578.95
  314.58  577.48  329.59  579.13  347.33   576.7  375.67  576.25  383.43  575.98
  394.13  576.19   423.7  576.82  445.16  582.48   451.3  585.82  457.43  592.13
  469.69  601.33  491.16  612.43  506.49  626.59  527.95  641.58  552.48  653.67
  580.08  664.21  592.34     672  619.94  686.41  653.67  700.41  696.59  714.08
#Mann= 3 , 0 , 0
       0      .1       0  375.67     .05       0  394.13      .1       0
Bank Sta=375.67,394.13
XS Rating Curve= 0 ,0
Exp/Cntr=0.3,0.1

Type RM Length L Ch R = 1 ,613.1852,93.31,91.44,90.91
XS GIS Cut Line= 5
     624154.7736      4342333.71     623931.4532     4342557.773
      623882.434    4342584.7836     623864.7734    4342595.7402
     623673.2309    4342779.2692
#Sta/Elev= 30
       0  665.83    21.5  654.69   36.86  648.82   49.14  642.71   73.71  634.72
  110.57  620.14  132.07  613.99  168.92  597.34  190.42  591.38  205.78  583.17
  214.99  580.07  239.56  578.11   351.7  574.55  363.48  573.72  371.21  574.53
  381.22  576.49  402.25  583.67  408.35   588.1  432.74  602.14  438.84  607.01
  460.18  617.98  472.38  626.46  487.62  635.04  545.56  661.24  551.66   663.3
   566.9  672.75  594.34  686.84  618.74  696.09  627.89   700.9  658.38  712.28
#Mann= 3 , 0 , 0
       0      .1       0   351.7     .05       0  371.21      .1       0
Bank Sta=351.7,371.21
XS Rating Curve= 0 ,0
Exp/Cntr=0.3,0.1

Type RM Length L Ch R = 1 ,521.7454,91.9,91.44,90.61
XS GIS Cut Line= 6
     624137.9108    4342322.2094     623923.0304    4342441.3513
      623854.206    4342491.3894     623835.0791    4342507.1948
     623817.6042    4342517.9387     623591.8097    4342734.9602
#Sta/Elev= 30
       0  662.63   36.86  645.33   49.14  640.46   61.42  635.85  101.35  625.23
  135.13  610.58  178.13  596.78  208.84  583.01   224.2  577.92  233.41  576.34
  333.79  573.41  342.79  572.95  349.76  573.57  358.56  576.23  370.29  578.13
  388.43  585.26  397.64  590.66  425.27  603.88  449.84  619.08  468.26  627.49
   474.4  629.29  498.96  643.67  545.02   666.1  554.23  671.49  584.93   685.4
  618.71  698.96  624.85  699.59  646.34  704.79  667.83  711.15  689.33  715.18
#Mann= 3 , 0 , 0
       0      .1       0  333.79     .05       0  349.76      .1       0
Bank Sta=333.79,349.76
XS Rating Curve= 0 ,0
Exp/Cntr=0.3,0.1

Type RM Length L Ch R = 1 ,430.3053,90.44,91.44,91.84
XS GIS Cut Line= 6
      624065.944    4342345.4928     623862.8975    4342364.3385
     623779.7863    4342434.6202     623773.5265    4342440.7174
     623768.7851    4342446.9034     623519.8429    4342662.9934
#Sta/Elev= 30
       0  633.44   60.87  616.12   82.18  611.57  103.48  609.15   118.7   605.3
  136.96  598.32  143.05  593.36  158.27  584.61  164.35   579.7  176.53  576.02
  299.06  572.26  312.76  571.79  315.23  572.14   329.3  575.95  350.66  584.76
  368.98  590.56  408.65  609.16  417.81  610.29  460.54  626.26  466.65  625.52
   469.7  626.22  515.48  639.99  530.75  640.24  552.11  643.74  558.22  643.51
  573.48  646.85  585.69  647.57  625.37  656.51  631.47  656.25  658.94  660.66
#Mann= 3 , 0 , 0
       0      .1       0  299.06     .05       0  315.23      .1       0
Bank Sta=299.06,315.23
XS Rating Curve= 0 ,0
Exp/Cntr=0.3,0.1

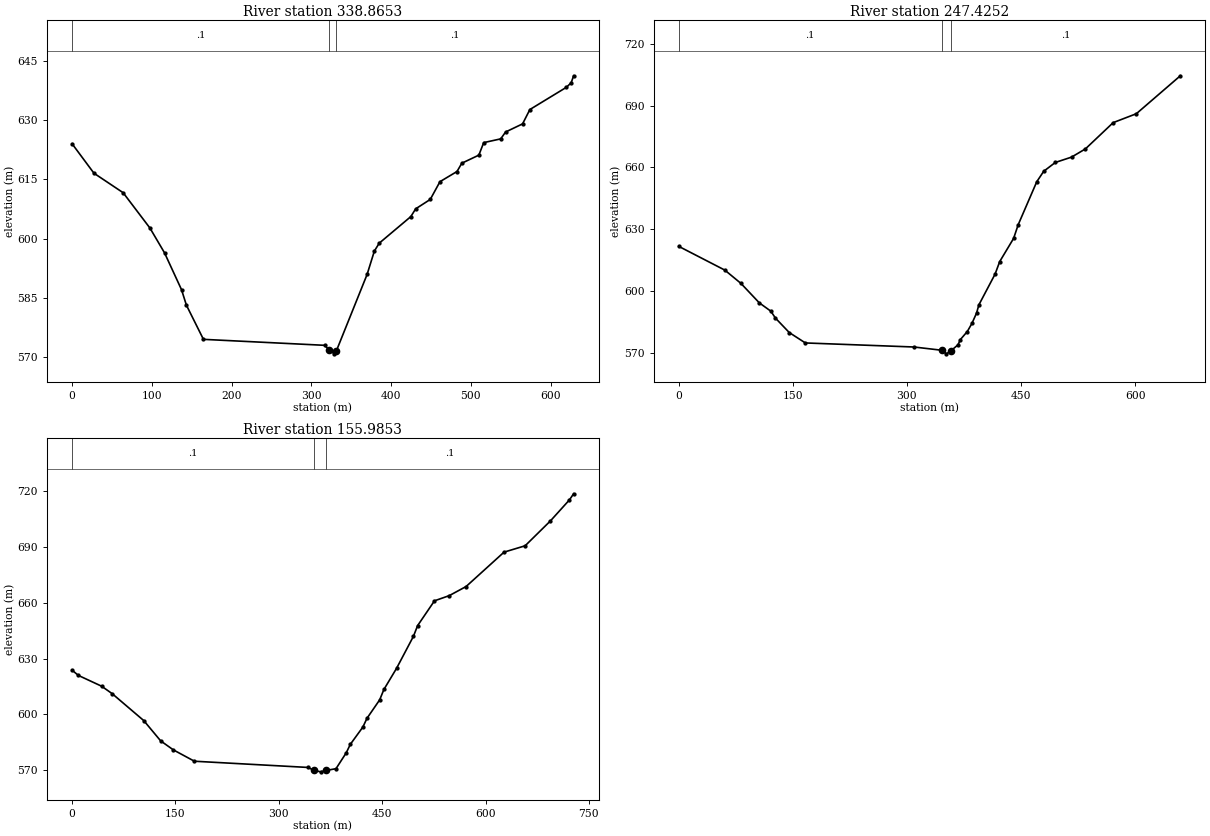
Type RM Length L Ch R = 1 ,338.8653,76.75,91.44,96.71
XS GIS Cut Line= 6
     624027.8439    4342337.0261     623868.0058    4342312.7119
     623730.1691    4342360.3466     623713.6309    4342373.4396
     623699.3954     4342387.456     623479.6261    4342561.3932
#Sta/Elev= 30
       0  624.04   27.45  616.57   64.06  611.63   97.62  602.69  115.92  596.41
  137.27  587.06  143.37  583.15  164.72  574.49  316.55  572.98  322.58   571.8
  328.61  570.82  331.46   571.6  369.91  590.92  379.05  596.86  385.14  598.85
  424.74  605.58  430.84  607.55  449.12  609.93   461.3  614.43  482.63     617
  488.72  619.11  510.04  621.15  516.14  624.32  537.46  625.27  543.56  627.01
  564.88  629.07  574.02   632.7  619.72  638.32  625.81  639.48  628.86  641.25
#Mann= 3 , 0 , 0
       0      .1       0  322.58     .05       0  331.46      .1       0
Bank Sta=322.58,331.46
XS Rating Curve= 0 ,0
Exp/Cntr=0.3,0.1

Type RM Length L Ch R = 1 ,247.4252,92.65,91.44,85.29
XS GIS Cut Line= 5
     624013.0272     4342324.326     623856.3935    4342277.7593
     623727.2918    4342297.5987     623651.0791    4342299.0644
     623401.3093    4342444.9763
#Sta/Elev= 30
       0   621.6   60.52  610.08    81.7  603.63  105.91  594.16  121.04  590.13
   127.1  586.77  145.25  579.76  166.45   574.7  309.27  572.73  345.86  571.15
  351.96  569.41  358.06  570.96   367.2  573.79  370.25  576.33  379.39  580.25
  385.48  584.18  391.57  589.21  394.61   593.2  415.93  608.14  422.02  614.23
  440.29  625.48  446.38  632.18  470.74     653  479.87  658.07   495.1  662.35
  516.41  664.94  534.68  668.93  571.22   681.7  601.67  686.02  659.52  704.45
#Mann= 3 , 0 , 0
       0      .1       0  345.86     .05       0  358.06      .1       0
Bank Sta=345.86,358.06
XS Rating Curve= 0 ,0
Exp/Cntr=0.3,0.1

Type RM Length L Ch R = 1 ,155.9853,134.34,155.99,149.78
XS GIS Cut Line= 6
     624015.1439     4342311.626     623699.0763    4342204.6009
     623682.9446    4342206.2408     623674.8714    4342215.6269
     623629.0264    4342231.1718     623356.8592    4342389.9428
#Sta/Elev= 30
       0  623.77    9.18  620.95   42.86  615.17   58.17  611.18  104.09  596.71
  128.58  585.84  146.95  581.02  177.56  574.92  342.39  571.59  350.74  570.11
  360.65  569.23  368.12  569.95     383  570.91  397.88  579.43  403.83  583.99
  421.94   593.2  428.06  597.99  446.41  607.84  452.53   613.4  470.88  624.73
  495.36  641.89  501.48  647.67  525.95  660.97  547.36  663.74  571.84  668.64
   626.9  687.08  657.49  690.48   694.2  703.83  721.73  715.08  727.85  718.38
#Mann= 3 , 0 , 0
       0      .1       0  350.74     .05       0  368.12      .1       0
Bank Sta=350.74,368.12
XS Rating Curve= 0 ,0
Exp/Cntr=0.3,0.1
LCMann Table=0

Chan Stop Cuts=-1
Use User Specified Reach Order=0
Composite Channel Slope=5